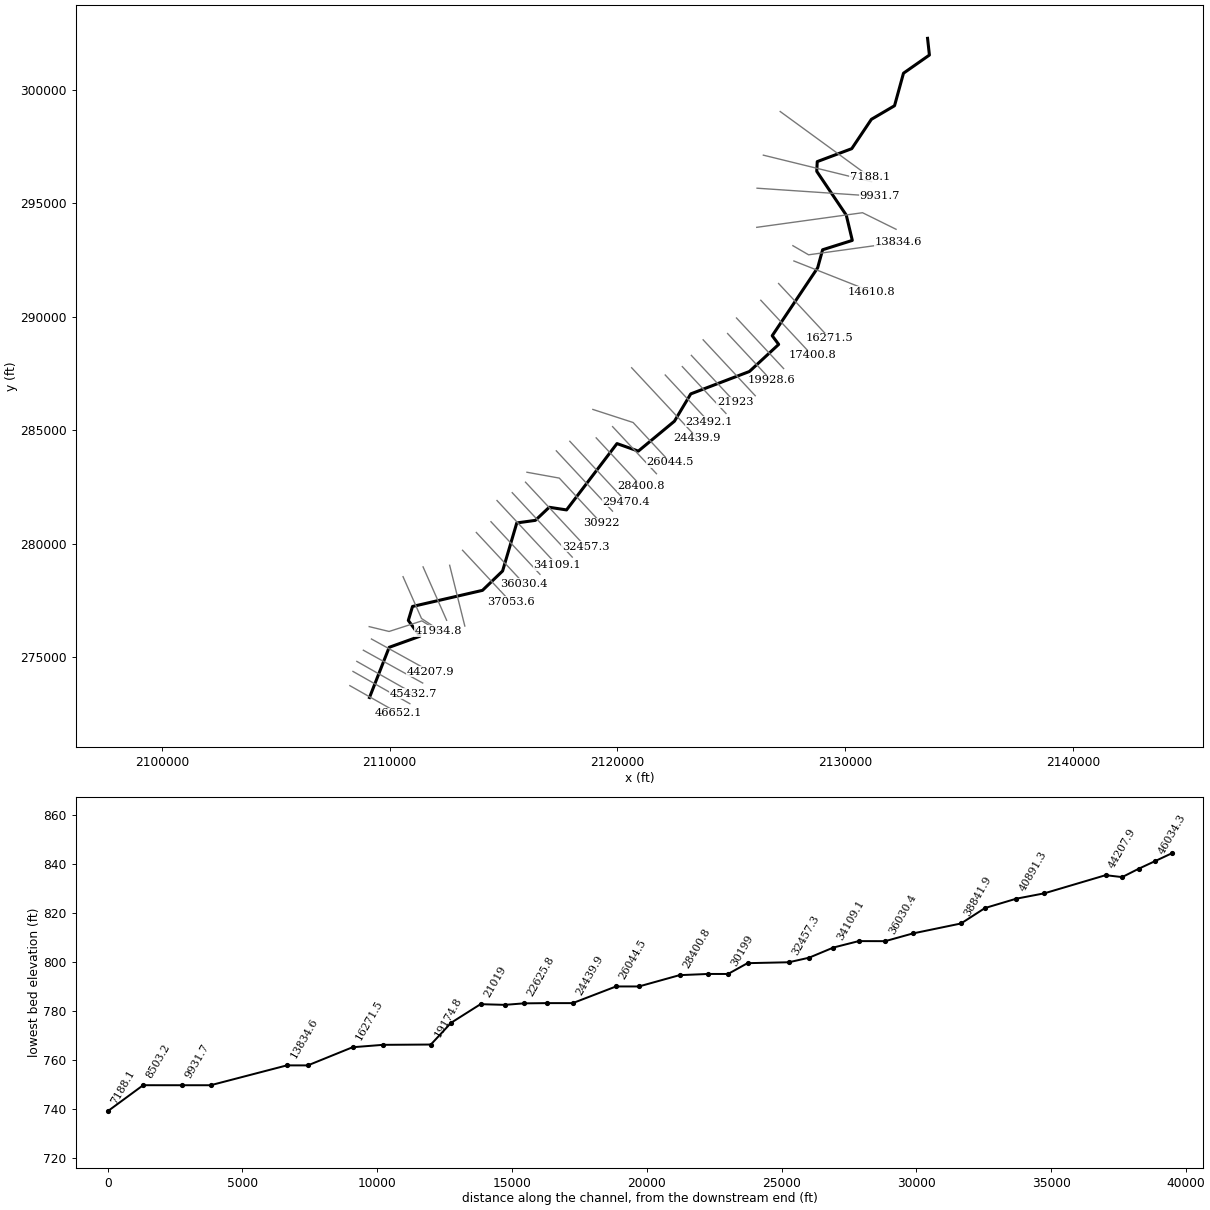
--- PTTRSNCR1.prj (project) ---

Proj Title=PTTRSNCR1
Current Plan=p01
Default Exp/Contr=0,0
English Units
Geom File=g01
Flow File=f01
Plan File=p01
BEGIN DESCRIPTION:
END DESCRIPTION:
DSS Export Rating Curves= 0
DSS Export Rating Curve Sorted= 0
DSS Export Volume Flow Curves= 0
DXF OffsetX= 0
DXF OffsetY= 0
DXF ScaleX= 0
DXF ScaleY= 0

--- PTTRSNCR1.p01 (plan) ---

Plan Title=Floodplain
Program Version=4.00
Geom File=g01
Flow File=f01
K Sum by GR=0
Std Step Tol=0.01
Critical Tol=0.01
Num of Std Step Trials=20
Max Error Tol=0.3
Flow Tol Ratio=0.001
Split Flow NTrial=30
Split Flow Tol=0.02
Split Flow Ratio=0.02
Log Output Level=0
Friction Slope Method=1
Unsteady Friction Slope Method=2
Unsteady Bridges Friction Slope Method=1
Global Log Level=0
CheckData=False
Run HTab=0
Run UNet=0
Run PostProcess=0
UNET Theta=0
UNET Theta Warmup=0
UNET ZTol=0
UNET ZSATol=0
UNET MxIter=0
UNET MaxInSteps=0
UNET DtIC=0
UNET DtMin=0
UNET MaxCRTS=0
UNET WFStab=0
UNET SFStab=0
UNET WFX=0
UNET SFX=0
UNET DSS MLevel=0
UNET DZMax Abort=0
UNET Convert EG Bridges=0
UNET Use Existing IB Tables=0
UNET Froude Limit=0
UNET Froude Power=0
Write IC File=0
Echo Input=False
Echo Output=False
Write Detailed=0

--- PTTRSNCR1.f01 (steady flow) ---

Flow Title=NFF Regression Equation
Program Version=4.00
Number of Profiles= 1
Profile Names=P100yr
River Rch & RM=PTTRSNCR1,Main            ,46652.1
   12422
River Rch & RM=PTTRSNCR1,Main            ,24439.9
   13510
River Rch & RM=PTTRSNCR1,Main            ,24439.9
   15706
River Rch & RM=PTTRSNCR1,Main            ,137.6
   17229
Boundary for River Rch & Prof#=PTTRSNCR1,Main            , 1
Up Type= 0
Dn Type= 1
Dn Known WS=750.75
DSS Import GetInterval= 0
DSS Import GetPeak= 0
DSS Import FillOption= 0

--- PTTRSNCR1.g01 (geometry) ---

Geom Title=USGS 10m DEM
Program Version=4.00

River Reach=PTTRSNCR1     ,Main
Reach XY= 30
     2109116.262      273236.746     2109980.652      275446.378
     2111327.288      275933.155     2110821.292      276630.666
     2111005.260      277244.607     2114078.921      277954.604
     2114961.304      278807.292     2115584.531      280922.862
     2116399.446      281035.907     2117008.468      281612.434
     2117769.648      281495.993     2119984.441      284416.545
     2120921.288      284084.668     2122507.902      285402.300
     2123223.772      286604.018     2125800.363      287590.548
     2127085.951      288783.818     2126801.459      289165.010
     2128798.003      292157.218     2129014.780      292950.283
     2130319.147      293362.461     2130054.837      294472.245
     2128757.095      296403.341     2128779.158      296830.958
     2130294.151      297401.083     2131156.380      298692.745
     2132173.464      299291.674     2132566.733      300723.859
     2133704.757      301522.686     2133623.757      302258.960

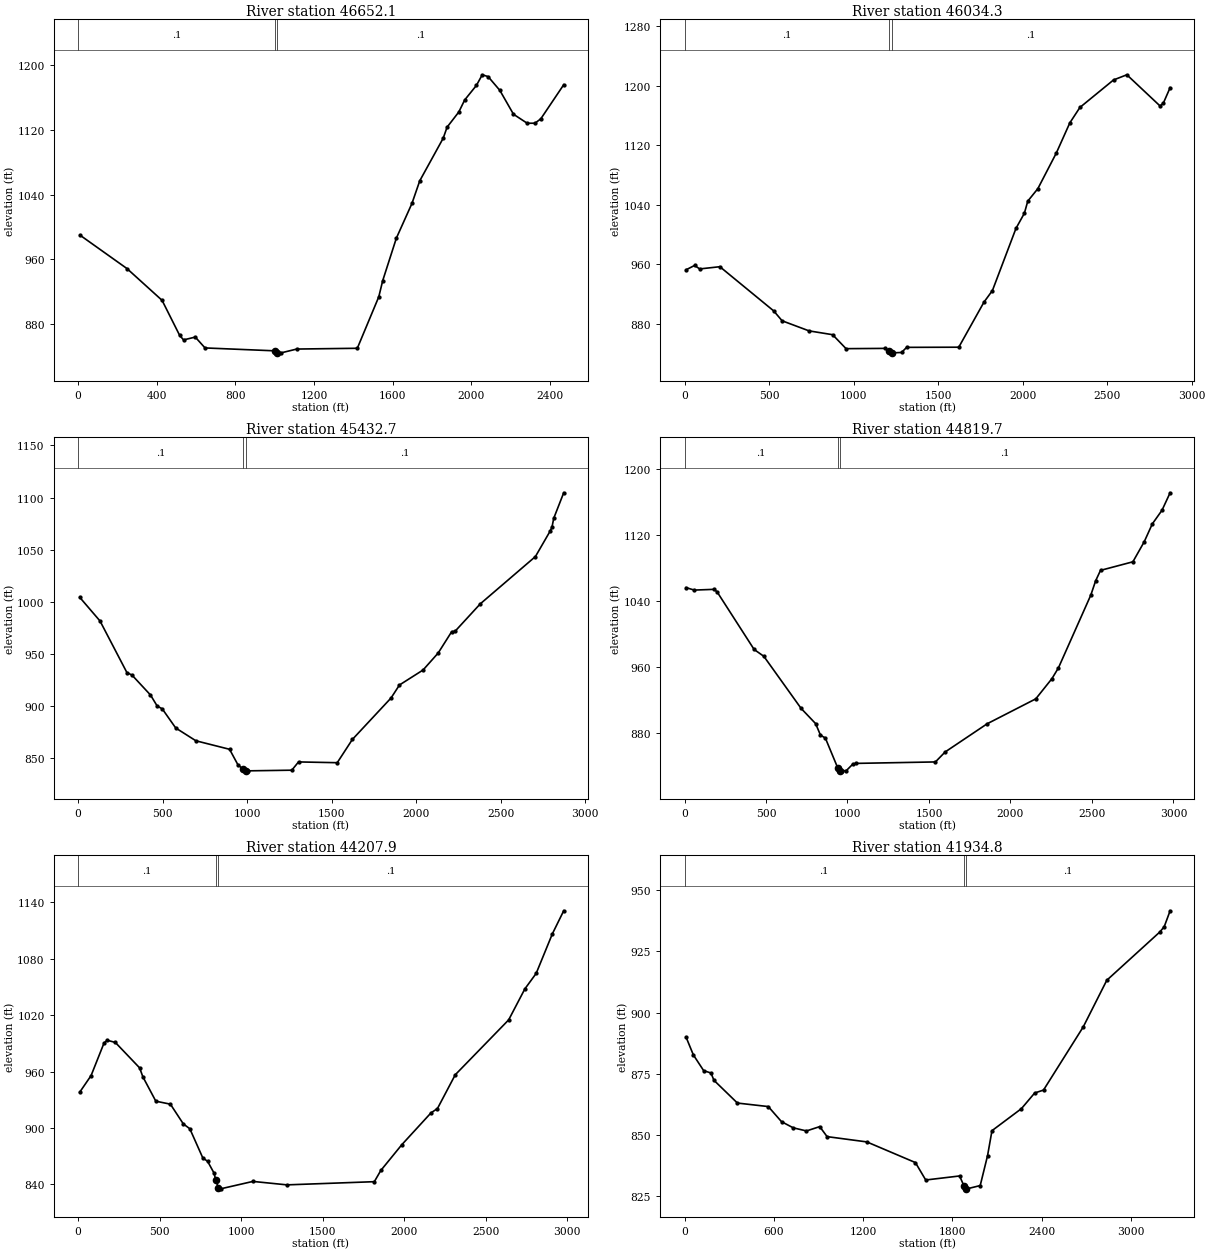
Type RM Length L Ch R = 1 ,46652.1,617.9,617.9,617.8
XS GIS Cut Line= 3
     2108253.465      273758.908     2110334.608      272576.027
     2110401.316      272538.111
#Sta/Elev= 30
     9.9  989.78   248.3  948.56   427.1  909.20   516.5  865.89   536.4  860.27
   596.0  863.77   645.6  850.34   999.2  846.77  1014.2  844.58  1033.0  844.27
  1112.5  848.96  1420.4  849.91  1529.7  913.61  1549.5  933.48  1619.1  986.16
  1698.5 1029.16  1738.2 1057.14  1857.4 1109.80  1877.3 1123.49  1936.9 1142.26
  1966.7 1157.10  2026.3 1175.08  2056.1 1188.26  2085.9 1186.01  2145.5 1169.00
  2215.0 1139.43  2284.6 1128.33  2324.3 1128.33  2354.1 1133.83  2470.5 1175.92
#Mann= 3 , 0 , 0
       0     0.1       0   999.2   0.045       0  1014.2     0.1       0
Bank Sta=   999.2,  1014.2
Exp/Cntr=0.3,0.1

Type RM Length L Ch R = 1 ,46034.3,605.2,601.6,597.4
XS GIS Cut Line= 3
     2108391.006      274384.682     2110588.846      273135.473
     2110888.289      272965.276
#Sta/Elev= 30
    10.0  952.88    59.7  958.63    89.6  953.93   209.0  956.92   527.5  897.47
   577.3  884.17   736.5  870.63   875.9  865.49   955.5  846.71  1184.4  847.06
  1212.3  843.11  1227.3  841.36  1234.2  841.09  1283.9  841.59  1313.8  848.46
  1622.3  848.67  1771.6  909.37  1821.4  924.87  1960.7 1008.46  2010.5 1028.86
  2030.4 1045.08  2090.1 1061.90  2199.6 1109.92  2279.2 1150.32  2338.9 1171.10
  2537.9 1208.09  2616.6 1215.03  2813.4 1173.00  2833.1 1177.22  2872.5 1197.71
#Mann= 3 , 0 , 0
       0     0.1       0  1212.3   0.045       0  1227.3     0.1       0
Bank Sta=  1212.3,  1227.3
Exp/Cntr=0.3,0.1

Type RM Length L Ch R = 1 ,45432.7,608.3,613,618.1
XS GIS Cut Line= 3
     2108560.153      274826.597     2110757.993      273577.388
     2111057.436      273407.191
#Sta/Elev= 30
    10.0 1004.27   129.4  981.70   288.6  932.21   318.5  929.85   428.0  910.74
   467.8  900.11   497.6  897.46   577.3  879.10   696.7  866.82   895.8  858.67
   945.5  843.76   977.8  839.32   992.8  838.16  1005.2  838.01  1264.0  838.63
  1303.8  846.56  1532.8  845.81  1622.3  868.11  1851.2  907.89  1901.0  920.34
  2040.4  934.68  2129.9  950.98  2209.6  971.40  2229.5  971.78  2378.8  998.10
  2705.2 1043.48  2793.8 1068.32  2803.6 1071.99  2813.4 1080.11  2872.5 1104.63
#Mann= 3 , 0 , 0
       0     0.1       0   977.8   0.045       0   992.8     0.1       0
Bank Sta=   977.8,   992.8
Exp/Cntr=0.3,0.1

Type RM Length L Ch R = 1 ,44819.7,611.8,611.8,611.8
XS GIS Cut Line= 2
     2108845.953      275318.614     2111452.164      273874.004
#Sta/Elev= 30
     9.9 1056.67    59.6 1053.70   178.8 1054.58   198.7 1051.88   427.1  981.71
   486.7  973.42   715.2  910.31   804.5  891.82   834.3  877.83   864.1  874.38
   941.1  837.69   956.1  834.85   963.5  834.60   993.3  834.97  1033.0  842.82
  1052.9  843.63  1539.6  845.40  1599.2  857.47  1857.4  891.68  2155.4  921.85
  2254.7  946.38  2294.4  959.38  2493.1 1047.58  2522.9 1065.00  2552.7 1077.59
  2751.4 1087.98  2820.9 1112.26  2870.5 1133.89  2930.1 1150.48  2979.8 1171.65
#Mann= 3 , 0 , 0
       0     0.1       0   941.1   0.045       0   956.1     0.1       0
Bank Sta=   941.1,   956.1
Exp/Cntr=0.3,0.1

Type RM Length L Ch R = 1 ,44207.9,2253.3,2273.1,2292.8
XS GIS Cut Line= 2
     2109201.862      275813.304     2111808.073      274368.694
#Sta/Elev= 30
     9.9  938.06    79.5  955.67   158.9  990.23   178.8  993.19   228.5  990.83
   377.4  963.83   397.3  954.34   476.8  928.47   566.2  925.31   645.6  904.33
   685.4  899.21   764.8  868.32   794.6  864.57   834.3  852.03   845.1  844.35
   860.1  836.64   874.1  835.39  1072.7  843.27  1281.3  839.61  1817.7  842.99
  1857.4  854.89  1986.5  882.30  2165.3  916.04  2205.1  920.68  2314.3  956.53
  2642.1 1014.85  2741.4 1047.72  2810.9 1064.20  2910.3 1106.24  2979.8 1130.69
#Mann= 3 , 0 , 0
       0     0.1       0   845.1   0.045       0   860.1     0.1       0
Bank Sta=   845.1,   860.1
Exp/Cntr=0.3,0.1

Type RM Length L Ch R = 1 ,41934.8,1075.6,1043.5,1002.5
XS GIS Cut Line= 4
     2109102.877      276357.267     2109976.096      276144.601
     2111416.737      276610.230     2112140.981      276163.464
#Sta/Elev= 30
     9.9  890.02    59.3  882.70   128.4  876.29   177.8  875.30   197.5  872.34
   355.5  863.03   562.9  861.60   651.8  855.43   730.8  852.91   819.7  851.64
   908.6  853.41   958.1  849.32  1225.3  847.16  1551.8  838.72  1621.1  831.60
  1848.7  833.25  1878.9  829.09  1893.9  828.03  1898.2  827.99  1987.3  829.33
  2036.7  841.55  2066.4  851.75  2264.3  860.75  2353.4  867.14  2412.8  868.34
  2679.9  894.15  2838.2  913.20  3194.5  932.91  3224.1  935.07  3263.7  941.58
#Mann= 3 , 0 , 0
       0     0.1       0  1878.9   0.045       0  1893.9     0.1       0
Bank Sta=  1878.9,  1893.9
Exp/Cntr=0.3,0.1

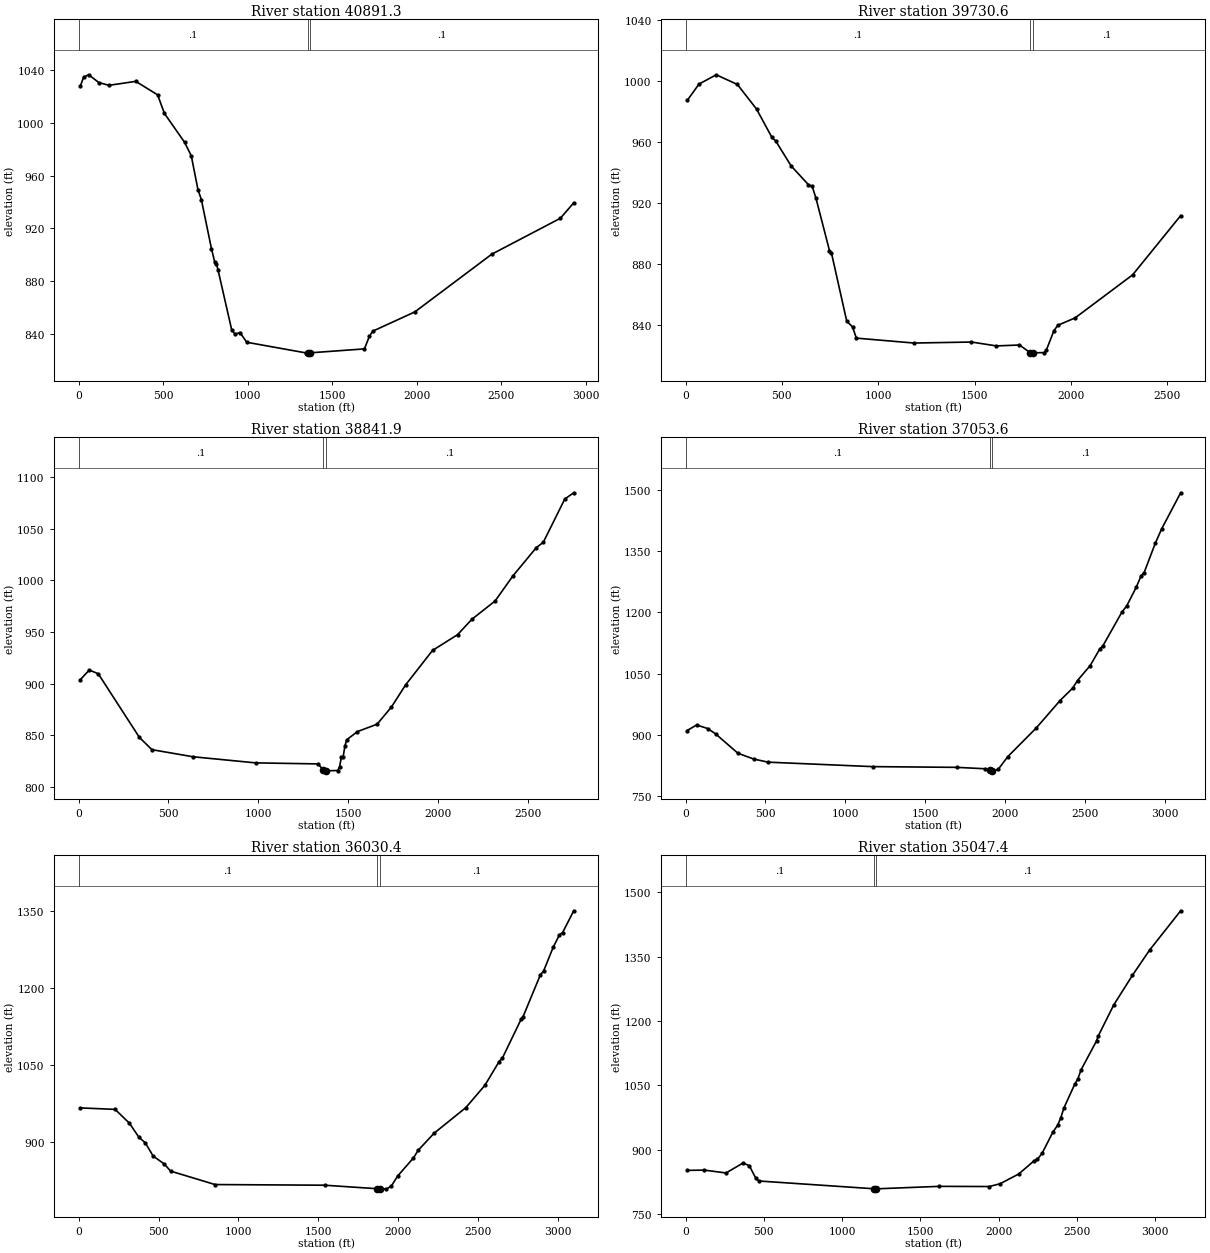
Type RM Length L Ch R = 1 ,40891.3,1160.9,1160.7,1160.5
XS GIS Cut Line= 3
     2110589.532      278555.411     2111399.473      276716.243
     2112167.978      276210.708
#Sta/Elev= 30
     9.9 1027.56    29.8 1034.46    59.7 1036.23   119.4 1030.38   179.1 1028.24
   338.3 1031.25   467.6 1021.02   507.4 1007.05   626.8  985.18   666.6  974.94
   706.3  949.22   726.2  941.80   785.9  904.72   805.8  894.23   815.8  893.06
   825.7  888.15   905.3  843.43   925.2  839.98   955.1  841.13   994.9  833.79
  1343.1  825.79  1354.8  825.79  1369.8  825.80  1691.3  828.78  1721.1  838.56
  1741.0  842.22  1989.7  856.79  2444.8  900.46  2850.4  927.62  2929.5  939.33
#Mann= 3 , 0 , 0
       0     0.1       0  1354.8   0.045       0  1369.8     0.1       0
Bank Sta=  1354.8,  1369.8
Exp/Cntr=0.3,0.1

Type RM Length L Ch R = 1 ,39730.6,892.7,888.7,884.6
XS GIS Cut Line= 2
     2111468.446      278988.037     2112503.584      276637.504
#Sta/Elev= 30
    10.0  987.33    69.7  997.80   159.3 1003.89   268.8  997.55   368.3  981.48
   448.0  962.92   467.9  960.56   547.5  944.30   637.1  932.04   657.0  930.89
   676.9  922.98   746.6  888.88   756.6  887.50   836.2  842.68   866.1  838.99
   886.0  831.61  1184.6  828.39  1483.3  829.05  1612.7  826.51  1732.2  827.10
  1787.8  822.10  1791.9  821.98  1802.8  821.99  1861.6  822.14  1871.5  823.72
  1911.3  836.56  1931.3  840.01  2020.8  844.83  2319.5  873.04  2568.4  911.73
#Mann= 3 , 0 , 0
       0     0.1       0  1787.8   0.045       0  1802.8     0.1       0
Bank Sta=  1787.8,  1802.8
Exp/Cntr=0.3,0.1

Type RM Length L Ch R = 1 ,38841.9,1776.9,1788.4,1799.8
XS GIS Cut Line= 2
     2112636.466      279058.242     2113302.088      276382.634
#Sta/Elev= 30
    10.0  903.95    59.7  913.19   109.5  909.55   338.4  848.06   408.1  836.16
   637.0  829.29   985.4  823.39  1333.8  822.38    1361  816.78  1373.6  815.68
    1376  815.68  1443.3  816.00  1453.2  819.67  1463.2  828.79  1473.1  829.21
  1483.1  839.68  1493.0  845.71  1552.8  853.65  1662.3  860.78  1741.9  877.39
  1821.5  898.92  1970.8  932.12  2110.2  947.34  2189.8  962.22  2319.2  979.92
  2418.7 1004.24  2548.1 1031.40  2587.9 1036.75  2707.4 1078.56  2757.2 1084.60
#Mann= 3 , 0 , 0
       0     0.1       0    1361   0.045       0    1376     0.1       0
Bank Sta=    1361,    1376
Exp/Cntr=0.3,0.1

Type RM Length L Ch R = 1 ,37053.6,1024.7,1023.1,1021.6
XS GIS Cut Line= 2
     2113202.336      279719.765     2115311.477      277451.053
#Sta/Elev= 30
     9.9  910.50    69.5  924.03   139.0  915.32   188.6  902.05   327.6  854.74
   426.9  840.47   516.3  832.89  1171.6  821.93  1697.8  820.15  1876.5  816.68
  1901.9  812.68  1916.9  811.63  1926.1  811.61  1955.9  814.99  2015.5  846.20
  2194.2  916.69  2343.1  983.98  2422.5 1014.58  2452.3 1033.07  2531.7 1069.73
  2591.3 1110.16  2611.2 1118.17  2730.3 1200.88  2760.1 1215.95  2819.7 1261.58
  2849.5 1289.10  2869.3 1297.81  2938.8 1369.43  2978.5 1404.64  3097.7 1493.36
#Mann= 3 , 0 , 0
       0     0.1       0  1901.9   0.045       0  1916.9     0.1       0
Bank Sta=  1901.9,  1916.9
Exp/Cntr=0.3,0.1

Type RM Length L Ch R = 1 ,36030.4,984.4,983,981.4
XS GIS Cut Line= 2
     2113807.521      280502.589     2115916.662      278233.877
#Sta/Elev= 30
     9.9  966.19   228.4  963.32   317.7  936.42   377.3  909.04   417.0  898.14
   466.6  872.32   536.1  856.84   575.8  842.98   853.8  816.82  1538.9  815.54
  1869.3  808.69  1884.3  808.58  1926.1  808.47  1955.9  813.54  1995.6  833.27
  2094.9  868.71  2124.7  883.61  2224.0  916.82  2422.5  966.67  2541.7 1010.11
  2631.0 1056.50  2650.9 1062.98  2770.0 1139.81  2780.0 1143.40  2889.2 1225.57
  2909.0 1232.73  2968.6 1278.76  3008.3 1303.45  3028.2 1307.96  3097.7 1350.31
#Mann= 3 , 0 , 0
       0     0.1       0  1869.3   0.045       0  1884.3     0.1       0
Bank Sta=  1869.3,  1884.3
Exp/Cntr=0.3,0.1

Type RM Length L Ch R = 1 ,35047.4,935.1,938.3,941.7
XS GIS Cut Line= 2
     2114450.414      280976.212     2116603.793      278659.915
#Sta/Elev= 30
     9.9  851.50   119.3  852.19   258.6  845.48   368.0  868.86   407.8  862.13
   447.5  834.00   467.4  826.81  1200.7  808.73  1213.3  808.49  1215.7  808.49
  1621.1  814.28  1939.4  813.86  2009.0  820.31  2128.3  843.12  2227.8  874.25
  2247.7  877.36  2277.5  891.37  2347.1  941.21  2377.0  956.70  2396.8  973.91
  2416.7  996.91  2486.3 1052.55  2506.2 1064.97  2526.1 1085.63  2625.6 1153.63
  2635.5 1164.37  2735.0 1237.06  2854.3 1306.09  2963.7 1364.78  3162.6 1456.66
#Mann= 3 , 0 , 0
       0     0.1       0  1200.7   0.045       0  1215.7     0.1       0
Bank Sta=  1200.7,  1215.7
Exp/Cntr=0.3,0.1

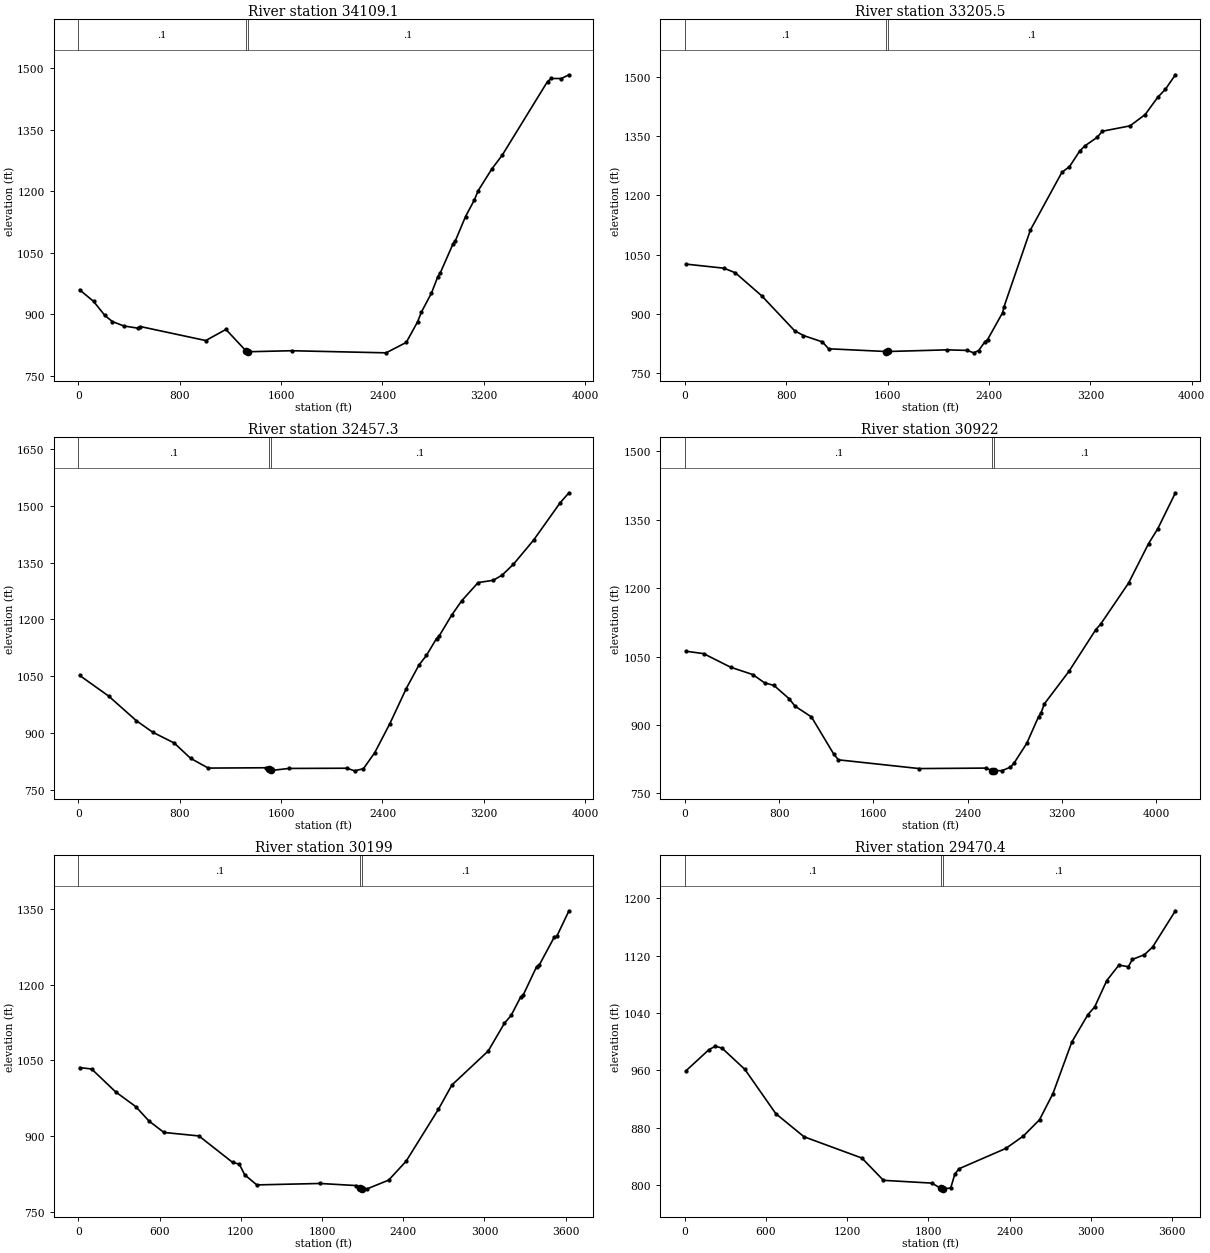
Type RM Length L Ch R = 1 ,34109.1,903.9,903.7,903.4
XS GIS Cut Line= 2
     2114715.485      281908.912     2117351.525      279073.437
#Sta/Elev= 30
    10.0  959.58   119.4  931.55   209.0  897.08   268.7  882.16   358.3  871.51
   467.8  866.14   487.7  870.09  1005.2  835.86  1164.4  863.00  1320.4  811.38
  1335.4  808.50  1682.0  811.04  2428.4  805.87  2587.6  831.31  2677.2  881.73
  2707.1  905.26  2786.7  951.83  2836.5  991.71  2856.4 1001.22  2955.9 1071.35
  2975.8 1079.89  3055.4 1138.57  3125.1 1178.97  3154.9 1201.52  3264.4 1255.31
  3344.0 1287.75  3702.3 1467.94  3732.2 1475.36  3811.8 1475.29  3871.5 1484.41
#Mann= 3 , 0 , 0
       0     0.1       0  1320.4   0.045       0  1335.4     0.1       0
Bank Sta=  1320.4,  1335.4
Exp/Cntr=0.3,0.1

Type RM Length L Ch R = 1 ,33205.5,748,748.2,748.3
XS GIS Cut Line= 2
     2115384.682      282253.898     2118020.722      279418.423
#Sta/Elev= 30
    10.0 1026.12   308.5 1015.83   398.1 1004.24   607.1  945.85   865.9  857.76
   935.5  845.57  1084.8  829.49  1134.6  812.02  1590.9  805.05  1605.9  805.13
  2070.1  809.29  2229.4  807.84  2279.1  801.72  2318.9  807.57  2368.7  829.99
  2388.6  834.94  2508.0  903.52  2518.0  917.56  2727.0 1112.49  2975.8 1258.44
  3035.5 1272.62  3115.1 1311.68  3154.9 1324.77  3254.5 1346.95  3294.3 1362.24
  3513.2 1375.85  3632.7 1404.48  3732.2 1448.32  3791.9 1468.20  3871.5 1505.09
#Mann= 3 , 0 , 0
       0     0.1       0  1590.9   0.045       0  1605.9     0.1       0
Bank Sta=  1590.9,  1605.9
Exp/Cntr=0.3,0.1

Type RM Length L Ch R = 1 ,32457.3,1535.4,1535.2,1535
XS GIS Cut Line= 2
     2115967.687      282716.784     2118603.727      279881.310
#Sta/Elev= 30
    10.0 1052.13   238.9  997.49   457.8  932.34   587.2  901.85   756.4  873.41
   885.8  832.84  1025.1  807.14  1482.9  808.02  1506.9  804.42  1521.9  800.86
  1662.1  806.21  2119.9  806.76  2179.6  799.86  2249.3  805.45  2338.8  847.87
  2458.3  924.83  2587.6 1017.47  2687.2 1079.32  2746.9 1105.00  2826.5 1149.75
  2846.4 1155.93  2945.9 1211.47  3025.6 1249.69  3154.9 1297.66  3274.4 1303.64
  3344.0 1317.26  3433.6 1346.11  3592.8 1410.01  3801.8 1508.50  3871.5 1535.02
#Mann= 3 , 0 , 0
       0     0.1       0  1506.9   0.045       0  1521.9     0.1       0
Bank Sta=  1506.9,  1521.9
Exp/Cntr=0.3,0.1

Type RM Length L Ch R = 1 ,30922,723.1,723.1,723.1
XS GIS Cut Line= 3
     2116030.799      283154.258     2117450.943      282897.013
     2119304.400      280903.329
#Sta/Elev= 30
    10.0 1061.78   159.3 1056.52   388.2 1026.79   577.3 1010.58   676.8  992.50
   756.5  986.81   885.9  957.51   935.6  941.31  1075.0  917.70  1264.1  836.30
  1303.9  823.63  1989.7  804.47  2556.0  805.53  2606.8  800.22  2621.8  799.53
  2625.5  799.49  2695.0  800.08  2764.6  807.66  2794.4  816.10  2903.7  860.11
  3003.0  918.11  3022.9  925.76  3052.7  946.38  3261.3 1017.68  3489.8 1109.37
  3529.6 1120.84  3768.0 1211.48  3936.9 1297.59  4016.4 1330.90  4165.4 1409.29
#Mann= 3 , 0 , 0
       0     0.1       0  2606.8   0.045       0  2621.8     0.1       0
Bank Sta=  2606.8,  2621.8
Exp/Cntr=0.3,0.1

Type RM Length L Ch R = 1 ,30199,728.6,728.6,728.6
XS GIS Cut Line= 3
     2117320.172      284096.789     2117473.128      283932.240
     2119787.960      281441.959
#Sta/Elev= 30
     9.8 1035.57    97.7 1032.86   274.4  987.60   423.5  958.32   522.9  929.29
   632.3  906.93   890.7  900.01  1139.3  847.57  1189.0  844.07  1228.8  822.88
  1318.2  802.90  1785.5  805.72  2053.9  801.56  2083.6  796.94  2098.6  795.19
  2133.4  795.08  2292.5  812.36  2421.7  849.93  2660.3  952.99  2759.7 1001.02
  3028.2 1068.54  3147.5 1123.36  3197.2 1139.01  3266.8 1174.99  3286.6 1179.48
  3386.1 1236.04  3405.9 1239.27  3515.3 1293.96  3535.2 1296.20  3624.7 1346.67
#Mann= 3 , 0 , 0
       0     0.1       0  2083.6   0.045       0  2098.6     0.1       0
Bank Sta=  2083.6,  2098.6
Exp/Cntr=0.3,0.1

Type RM Length L Ch R = 1 ,29470.4,1069.6,1069.6,1069.6
XS GIS Cut Line= 3
     2117913.665      284517.713     2118066.620      284353.165
     2120381.453      281862.884
#Sta/Elev= 30
     9.8  959.77   175.8  988.59   224.7  993.79   274.4  991.16   443.4  961.52
   672.0  899.81   880.8  867.60  1308.3  837.96  1467.3  806.93  1825.2  803.07
  1892.1  795.60  1904.8  795.09  1907.1  795.09  1964.4  796.23  1994.2  815.23
  2024.1  822.92  2372.0  851.42  2501.3  868.67  2620.6  891.34  2720.0  927.88
  2859.2  999.61  2978.5 1037.89  3028.2 1048.47  3117.6 1085.29  3207.1 1106.73
  3276.7 1104.56  3306.5 1114.58  3396.0 1121.33  3455.6 1131.75  3624.7 1182.42
#Mann= 3 , 0 , 0
       0     0.1       0  1892.1   0.045       0  1907.1     0.1       0
Bank Sta=  1892.1,  1907.1
Exp/Cntr=0.3,0.1

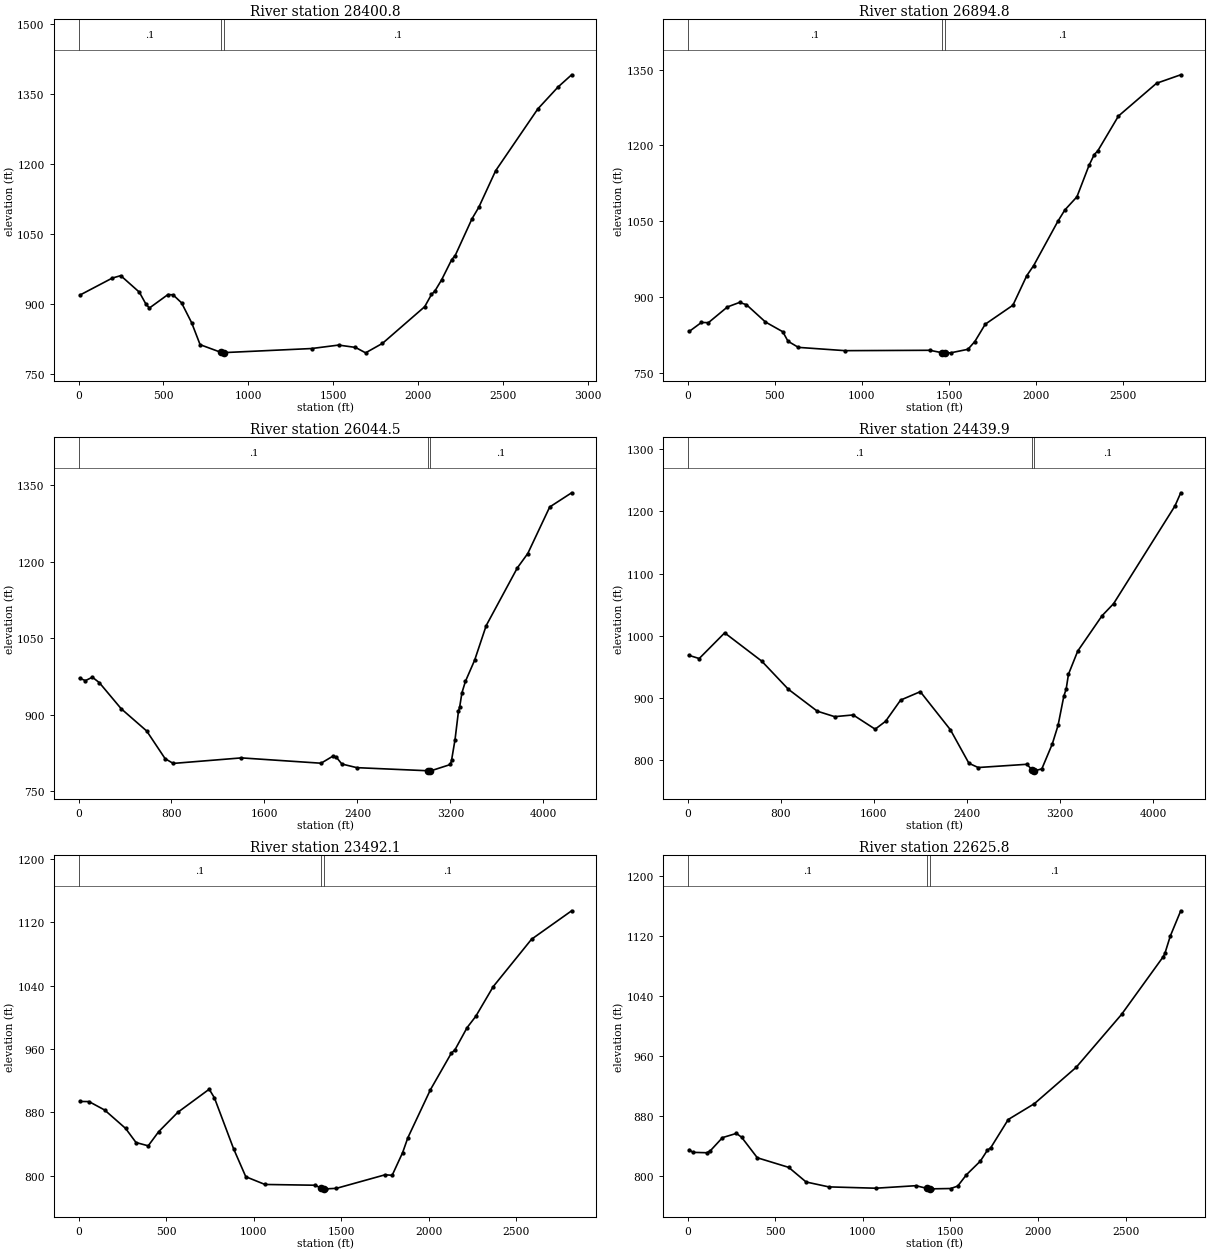
Type RM Length L Ch R = 1 ,28400.8,1500.1,1506,1512.4
XS GIS Cut Line= 2
     2119070.712      284668.077     2121048.241      282540.665
#Sta/Elev= 30
     9.9  918.75   198.9  954.91   248.7  960.14   358.1  924.79   397.9  898.56
   417.8  890.76   527.2  919.67   557.0  918.98   606.8  901.92   666.5  859.07
   716.2  812.13   840.8  795.40   855.8  795.07  1372.7  803.83  1531.9  811.24
  1631.3  806.24  1691.0  794.60  1790.5  814.94  2039.2  893.64  2079.0  919.73
  2098.8  926.94  2138.6  951.08  2198.3  994.58  2218.2 1002.86  2317.7 1082.09
  2357.5 1106.59  2456.9 1185.08  2705.6 1317.76  2825.0 1364.83  2904.6 1390.86
#Mann= 3 , 0 , 0
       0     0.1       0   840.8   0.045       0   855.8     0.1       0
Bank Sta=   840.8,   855.8
Exp/Cntr=0.3,0.1

Type RM Length L Ch R = 1 ,26894.8,855.7,850.3,844.3
XS GIS Cut Line= 2
     2119791.783      285162.799     2121718.268      283090.562
#Sta/Elev= 30
     9.9  832.45    79.4  850.11   119.1  849.58   228.3  880.72   297.8  889.65
   337.5  885.14   446.7  850.91   546.0  831.69   575.8  812.96   635.4  800.80
   903.4  794.30  1389.9  795.03  1459.5  790.21  1474.5  790.06  1509.0  789.99
  1608.3  796.98  1648.0  812.40  1707.6  846.59  1866.4  884.15  1945.8  942.53
  1985.5  962.54  2124.5 1050.15  2164.2 1072.37  2233.7 1098.47  2303.2 1160.69
  2333.0 1181.95  2352.9 1189.01  2472.0 1258.16  2690.4 1322.88  2829.4 1339.68
#Mann= 3 , 0 , 0
       0     0.1       0  1459.5   0.045       0  1474.5     0.1       0
Bank Sta=  1459.5,  1474.5
Exp/Cntr=0.3,0.1

Type RM Length L Ch R = 1 ,26044.5,1604.9,1604.6,1604.5
XS GIS Cut Line= 3
     2118925.687      285920.075     2120692.873      285344.576
     2122316.428      283598.187
#Sta/Elev= 30
     9.9  971.58    59.6  966.90   119.3  973.55   178.9  962.95   367.7  911.61
   586.4  868.18   745.4  813.79   815.0  804.54  1401.4  815.37  2087.0  804.93
  2186.4  818.47  2216.2  817.34  2265.9  803.37  2395.0  796.22    3009  790.11
    3024  790.00  3030.9  789.99  3199.8  802.42  3209.7  810.58  3239.6  851.04
  3269.4  907.14  3279.3  914.74  3299.2  943.15  3329.0  965.33  3408.5 1007.02
  3507.8 1074.74  3776.1 1188.04  3865.5 1216.04  4054.3 1307.29  4243.0 1335.15
#Mann= 3 , 0 , 0
       0     0.1       0    3009   0.045       0    3024     0.1       0
Bank Sta=    3009,    3024
Exp/Cntr=0.3,0.1

Type RM Length L Ch R = 1 ,24439.9,947.8,947.8,947.8
XS GIS Cut Line= 2
     2120629.012      287755.169     2123514.182      284651.716
#Sta/Elev= 30
     9.9  968.80    99.5  963.61   318.3 1004.84   636.6  959.47   865.4  914.26
  1114.1  879.03  1263.3  870.22  1422.4  872.98  1611.4  850.12  1700.9  862.76
  1830.2  896.85  1999.3  910.36  2258.0  849.16  2417.1  795.33  2496.7  788.51
  2914.5  793.71  2962.6  784.31  2977.6  783.21  2984.1  783.19  3043.8  786.44
  3133.3  826.27  3183.0  856.14  3232.8  903.32  3252.7  914.52  3272.6  938.39
  3352.1  975.61  3561.0 1032.34  3660.5 1051.81  4187.7 1208.76  4237.4 1229.87
#Mann= 3 , 0 , 0
       0     0.1       0  2962.6   0.045       0  2977.6     0.1       0
Bank Sta=  2962.6,  2977.6
Exp/Cntr=0.3,0.1

Type RM Length L Ch R = 1 ,23492.1,860.3,866.3,872.4
XS GIS Cut Line= 2
     2122103.735      287435.554     2124020.249      285374.042
#Sta/Elev= 30
     9.9  893.52    59.7  893.40   149.2  882.74   268.5  859.56   328.2  841.70
   397.8  837.51   457.5  855.35   566.9  879.86   746.0  909.00   775.8  898.11
   885.2  833.80   954.8  798.49  1064.2  788.72  1352.7  787.74  1383.8  783.89
  1398.8  783.27  1412.4  783.19  1472.0  783.81  1750.5  800.96  1790.3  800.26
  1850.0  828.92  1879.8  847.68  2009.1  908.51  2128.5  954.72  2148.4  958.64
  2218.0  986.79  2267.7 1001.11  2367.2 1038.59  2586.0 1098.45  2814.8 1134.37
#Mann= 3 , 0 , 0
       0     0.1       0  1383.8   0.045       0  1398.8     0.1       0
Bank Sta=  1383.8,  1398.8
Exp/Cntr=0.3,0.1

Type RM Length L Ch R = 1 ,22625.8,708.6,702.8,696.8
XS GIS Cut Line= 2
     2122853.935      287805.278     2124770.450      285743.766
#Sta/Elev= 30
     9.9  835.15    29.8  831.77   109.4  831.25   129.3  833.82   198.9  851.42
   278.5  857.05   308.3  851.88   397.8  824.53   576.9  811.74   676.3  792.23
   805.6  785.70  1074.2  783.93  1302.9  787.28  1366.7  783.70  1381.7  783.17
  1392.5  783.09  1501.9  783.52  1541.7  786.79  1591.4  801.87  1671.0  820.10
  1710.7  834.49  1730.6  838.07  1830.1  875.57  1979.3  896.72  2218.0  945.23
  2476.6 1015.70  2715.3 1092.92  2725.2 1097.88  2755.1 1120.32  2814.8 1154.03
#Mann= 3 , 0 , 0
       0     0.1       0  1366.7   0.045       0  1381.7     0.1       0
Bank Sta=  1366.7,  1381.7
Exp/Cntr=0.3,0.1

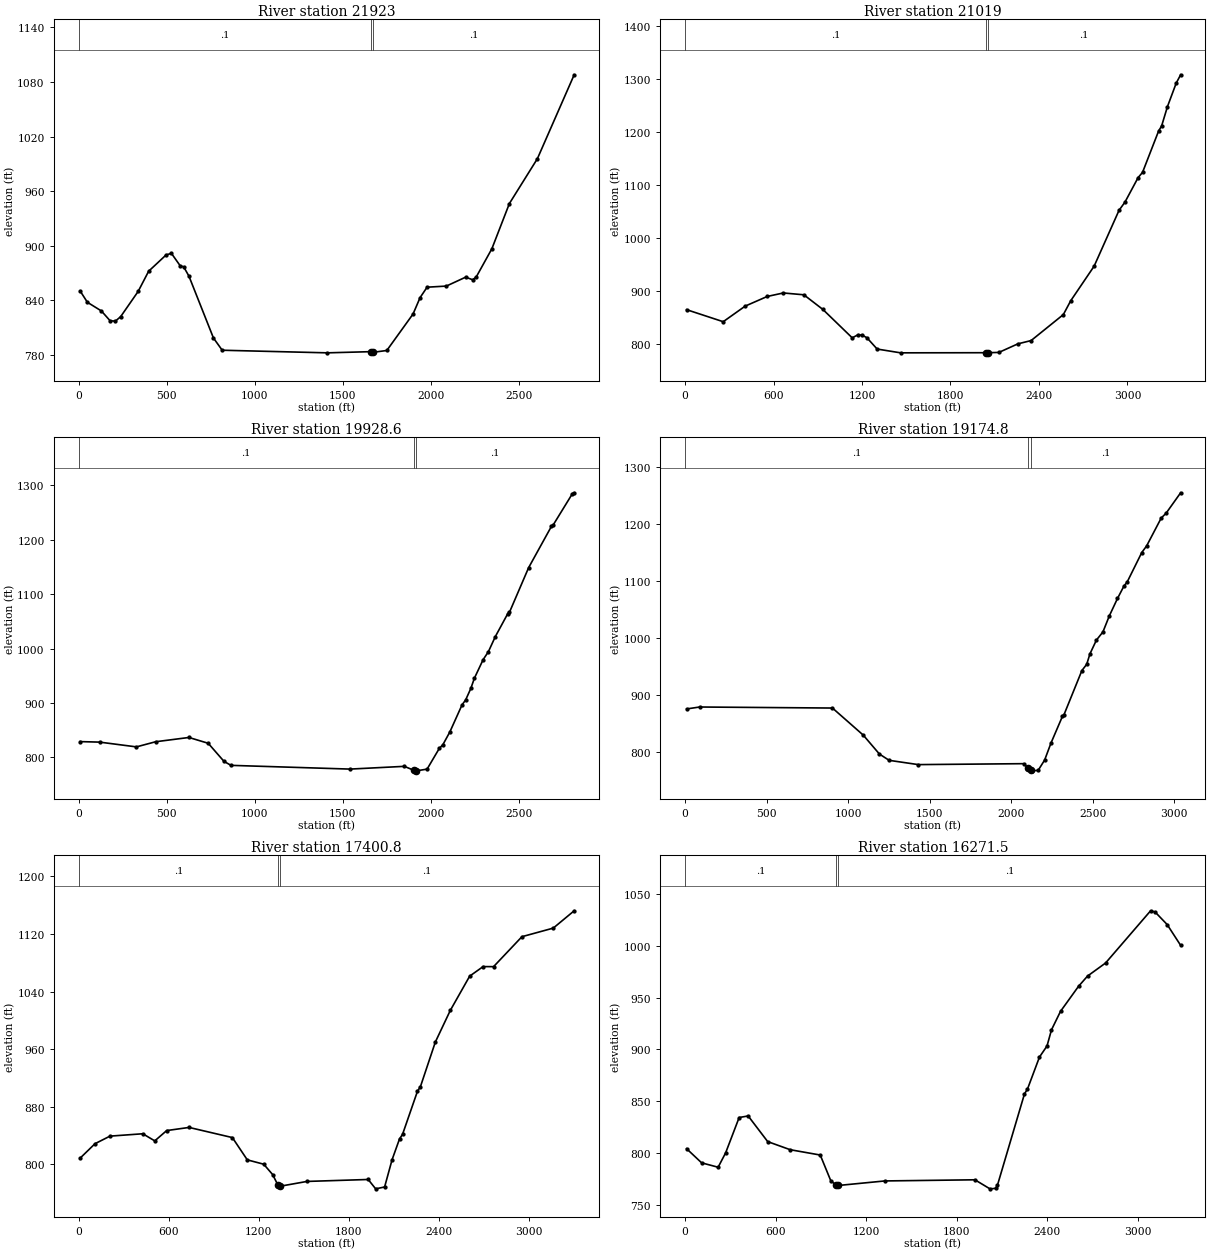
Type RM Length L Ch R = 1 ,21923,902.6,904,905.2
XS GIS Cut Line= 2
     2123250.913      288299.977     2125167.428      286238.465
#Sta/Elev= 30
     9.9  850.03    49.7  838.02   129.3  828.48   179.0  817.65   208.9  817.33
   238.7  822.22   338.2  849.97   397.8  872.14   497.3  890.08   527.1  891.73
   576.9  878.08   596.8  876.91   626.6  866.71   765.9  798.72   815.6  785.34
  1412.4  782.48  1658.7  783.77  1673.7  783.11  1750.5  785.06  1899.7  825.15
  1939.5  843.12  1979.3  854.58  2088.7  855.79  2198.1  865.57  2237.9  862.78
  2257.8  865.56  2347.3  896.78  2446.8  946.44  2605.9  995.72  2814.8 1087.86
#Mann= 3 , 0 , 0
       0     0.1       0  1658.7   0.045       0  1673.7     0.1       0
Bank Sta=  1658.7,  1673.7
Exp/Cntr=0.3,0.1

Type RM Length L Ch R = 1 ,21019,1091.8,1090.4,1089.2
XS GIS Cut Line= 2
     2123768.353      288984.786     2126056.810      286523.191
#Sta/Elev= 30
     9.9  864.24   258.5  841.51   407.7  870.96   556.9  889.15   666.2  895.76
   805.5  892.30   934.7  864.61  1133.6  811.04  1173.4  817.02  1203.2  815.77
  1233.0  811.31  1302.6  789.90  1461.7  782.76  2037.7  783.00  2052.7  783.02
  2128.0  783.53  2257.3  799.75  2346.8  805.91  2565.5  854.97  2615.2  880.92
  2774.3  946.35  2943.4 1051.85  2983.2 1067.12  3072.7 1113.55  3102.5 1123.28
  3211.9 1201.63  3231.8 1210.73  3271.5 1247.38  3331.2 1291.92  3361.0 1307.52
#Mann= 3 , 0 , 0
       0     0.1       0  2037.7   0.045       0  2052.7     0.1       0
Bank Sta=  2037.7,  2052.7
Exp/Cntr=0.3,0.1

Type RM Length L Ch R = 1 ,19928.6,753.8,753.8,753.8
XS GIS Cut Line= 2
     2124842.421      289261.345     2126758.936      287199.833
#Sta/Elev= 30
     9.9  828.90   119.4  827.97   328.2  819.21   437.6  828.67   626.6  836.52
   736.0  825.85   825.5  792.65   865.3  785.26  1541.7  778.39  1850.0  783.44
  1903.3  776.31  1918.3  775.18  1979.3  778.31  2048.9  816.55  2068.8  823.10
  2108.6  846.65  2178.2  896.69  2198.1  905.37  2227.9  926.72  2247.8  945.29
  2297.6  979.58  2327.4  994.11  2367.2 1022.13  2436.8 1063.66  2446.8 1066.32
  2556.2 1148.75  2685.5 1224.54  2695.4 1227.07  2804.8 1284.75  2814.8 1286.34
#Mann= 3 , 0 , 0
       0     0.1       0  1903.3   0.045       0  1918.3     0.1       0
Bank Sta=  1903.3,  1918.3
Exp/Cntr=0.3,0.1

Type RM Length L Ch R = 1 ,19174.8,1771.4,1774,1758.9
XS GIS Cut Line= 2
     2125233.031      289945.982     2127302.323      287720.134
#Sta/Elev= 30
     9.9  875.21    89.4  878.59   903.8  876.77  1092.5  829.16  1191.8  795.82
  1251.4  784.77  1430.2  777.25  2075.8  778.90  2103.8  771.22  2118.8  766.93
  2125.4  766.29  2165.1  767.09  2204.9  785.21  2244.6  815.62  2314.1  862.08
  2324.0  865.26  2433.3  942.59  2463.1  953.79  2483.0  972.18  2522.7  996.38
  2562.4 1010.60  2602.1 1039.16  2651.8 1069.54  2691.5 1091.41  2711.4 1098.62
  2800.8 1150.38  2830.6 1162.04  2920.0 1211.05  2949.8 1219.49  3039.1 1255.48
#Mann= 3 , 0 , 0
       0     0.1       0  2103.8   0.045       0  2118.8     0.1       0
Bank Sta=  2103.8,  2118.8
Exp/Cntr=0.3,0.1

Type RM Length L Ch R = 1 ,17400.8,1128.7,1129.3,1129.9
XS GIS Cut Line= 2
     2126300.409      290727.277     2128547.503      288310.173
#Sta/Elev= 30
     9.9  808.78   109.3  828.87   208.8  839.35   427.4  842.64   507.0  832.74
   586.5  847.07   735.6  851.43  1023.9  837.34  1123.3  806.39  1232.6  800.38
  1292.3  785.94    1328  771.04    1343  769.84  1520.9  776.46  1928.5  779.16
  1978.2  766.17  2037.8  768.74  2087.5  806.56  2137.2  835.51  2157.1  841.71
  2256.5  901.59  2276.4  908.07  2375.8  970.05  2475.2 1013.86  2604.4 1061.49
  2693.9 1074.74  2763.5 1074.65  2952.4 1116.25  3161.1 1128.17  3300.3 1152.23
#Mann= 3 , 0 , 0
       0     0.1       0    1328   0.045       0    1343     0.1       0
Bank Sta=    1328,    1343
Exp/Cntr=0.3,0.1

Type RM Length L Ch R = 1 ,16271.5,1650.5,1660.7,1670.8
XS GIS Cut Line= 2
     2127082.211      291463.975     2129318.184      289058.835
#Sta/Elev= 30
    10.0  803.94   109.5  790.31   218.9  786.05   268.7  799.97   358.2  834.10
   418.0  835.59   547.3  810.82   696.6  802.98   895.6  797.85   965.3  773.08
  1001.3  768.71  1016.3  768.45  1323.5  772.82  1920.6  773.93  2020.1  765.19
  2059.9  765.66  2069.9  768.68  2249.0  856.90  2268.9  861.56  2348.5  892.53
  2398.3  903.16  2428.1  918.80  2487.8  936.62  2607.3  960.84  2667.0  970.73
  2786.4  983.33  3084.9 1033.79  3114.8 1032.60  3194.4 1020.52  3283.9 1000.40
#Mann= 3 , 0 , 0
       0     0.1       0  1001.3   0.045       0  1016.3     0.1       0
Bank Sta=  1001.3,  1016.3
Exp/Cntr=0.3,0.1

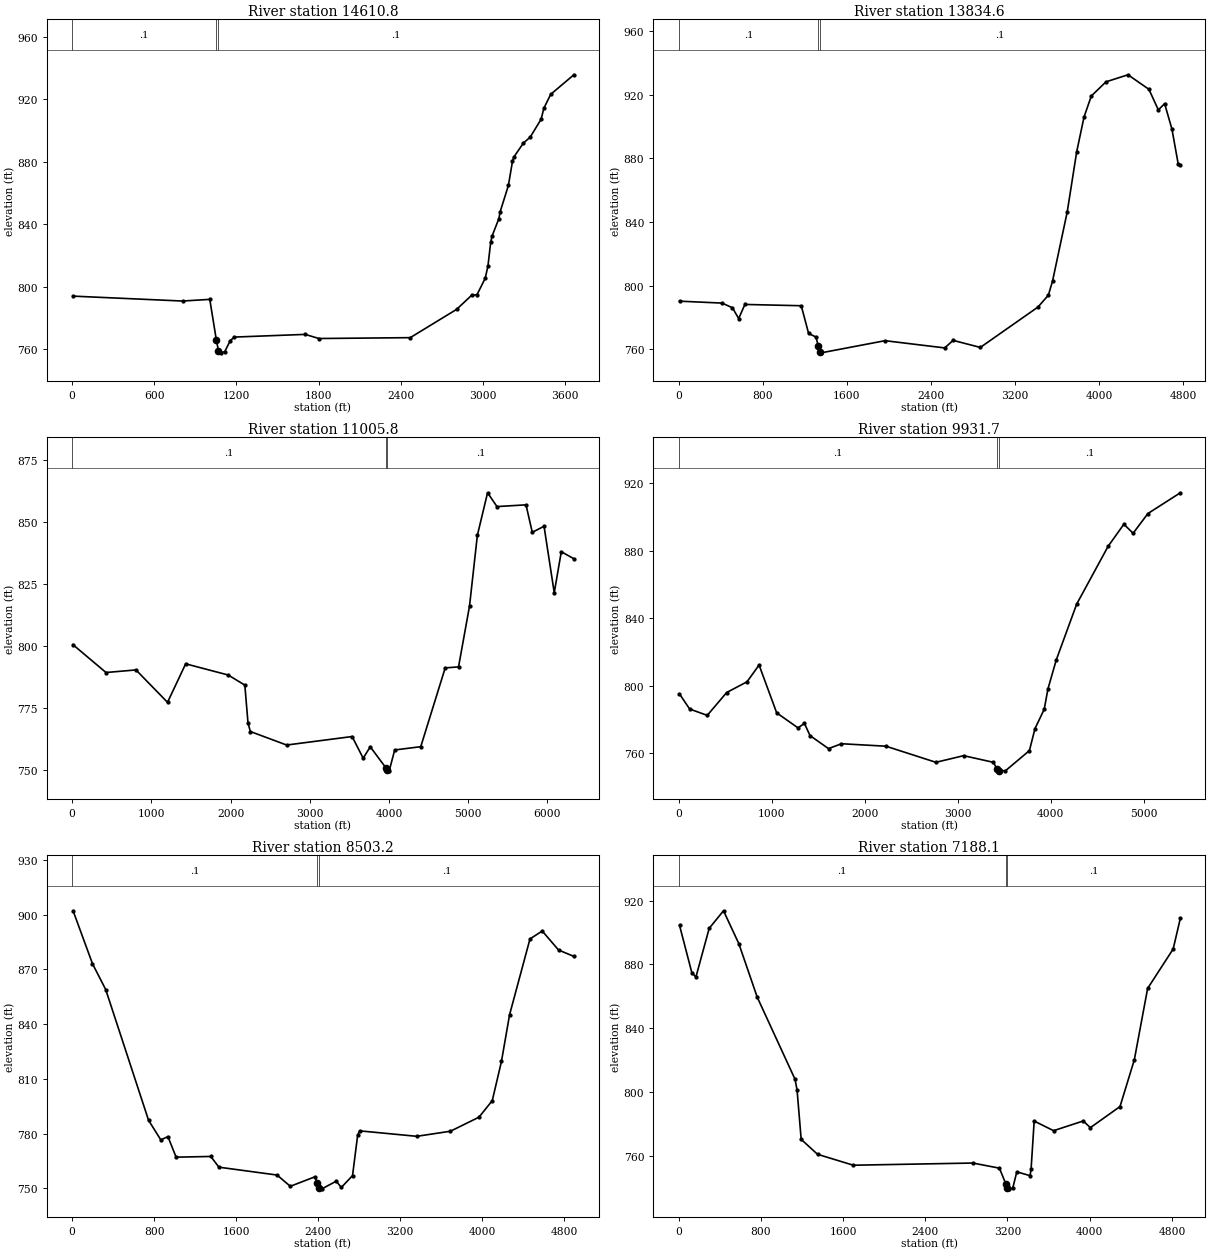
Type RM Length L Ch R = 1 ,14610.8,763.1,776.2,789.4
XS GIS Cut Line= 2
     2127754.680      292456.387     2131161.470      291106.788
#Sta/Elev= 30
    10.0  794.04   806.6  790.91  1005.7  791.98  1054.1  765.73  1069.1  759.11
  1085.4  757.78  1115.2  758.57  1155.1  765.59  1184.9  767.86  1702.7  769.58
  1802.3  766.94  2469.5  767.49  2808.0  785.57  2917.6  794.56  2957.4  795.00
  3017.1  805.51  3037.0  813.29  3057.0  828.46  3066.9  832.40  3116.7  843.60
  3126.7  848.15  3186.4  864.82  3216.3  880.37  3226.2  883.01  3295.9  891.94
  3345.7  895.74  3425.4  907.22  3445.3  914.19  3495.1  923.07  3664.4  935.61
#Mann= 3 , 0 , 0
       0     0.1       0  1054.1   0.045       0  1069.1     0.1       0
Bank Sta=  1054.1,  1069.1
Exp/Cntr=0.3,0.1

Type RM Length L Ch R = 1 ,13834.6,2830.2,2828.8,2827.4
XS GIS Cut Line= 3
     2127709.345      293129.295     2128399.703      292728.155
     2132333.677      293273.235
#Sta/Elev= 30
     9.9  790.28   414.0  789.07   512.6  786.12   571.7  779.36   630.9  788.22
  1166.7  787.41  1236.4  769.98  1306.1  767.74  1330.1  761.83  1345.1  758.24
  1355.9  757.79  1963.0  765.43  2530.4  760.88  2610.0  765.63  2868.8  761.19
  3416.3  786.55  3515.8  794.06  3555.6  803.02  3695.0  846.45  3784.6  884.12
  3854.3  906.00  3923.9  919.30  4063.3  928.20  4272.3  932.64  4471.4  923.51
  4561.0  910.54  4620.7  914.49  4690.4  898.44  4750.1  876.44  4770.0  876.04
#Mann= 3 , 0 , 0
       0     0.1       0  1330.1   0.045       0  1345.1     0.1       0
Bank Sta=  1330.1,  1345.1
Exp/Cntr=0.3,0.1

Type RM Length L Ch R = 1 ,11005.8,1078.9,1074,1069.2
XS GIS Cut Line= 3
     2126122.423      293937.665     2130767.358      294581.255
     2132240.354      293852.201
#Sta/Elev= 30
    10.0  800.56   428.1  789.31   806.4  790.35  1204.7  777.29  1433.7  792.81
  1971.3  788.29  2180.4  784.23  2220.2  769.03  2250.1  765.53  2708.1  760.09
  3534.4  763.51  3673.8  754.78  3763.4  759.37  3957.8  751.02  3972.8  749.92
  4002.3  749.69  4072.0  758.10  4400.6  759.42  4709.1  791.17  4877.4  791.57
  5016.0  816.06  5115.0  844.58  5243.8  861.73  5362.6  856.17  5728.9  856.87
  5808.1  845.79  5956.6  848.24  6085.3  821.48  6174.4  837.99  6332.9  835.15
#Mann= 3 , 0 , 0
       0     0.1       0  3957.8   0.045       0  3972.8     0.1       0
Bank Sta=  3957.8,  3972.8
Exp/Cntr=0.3,0.1

Type RM Length L Ch R = 1 ,9931.7,1431.9,1428.6,1425.1
XS GIS Cut Line= 2
     2126136.240      295660.704     2131519.651      295296.634
#Sta/Elev= 30
    10.0  795.24   119.5  786.28   308.6  782.52   517.7  796.05   736.7  802.41
   866.1  812.33  1055.2  784.03  1284.2  775.13  1353.9  777.75  1413.6  770.57
  1612.7  762.84  1752.1  765.73  2230.0  764.27  2767.5  754.74  3066.2  758.67
  3384.8  754.74  3426.7  750.64  3441.7  749.85  3514.2  749.69  3773.0  761.67
  3832.7  774.66  3932.3  786.16  3972.1  798.17  4061.7  815.35  4280.7  848.33
  4619.2  882.59  4788.4  895.66  4888.0  890.33  5047.3  902.00  5395.7  914.28
#Mann= 3 , 0 , 0
       0     0.1       0  3426.7   0.045       0  3441.7     0.1       0
Bank Sta=  3426.7,  3441.7
Exp/Cntr=0.3,0.1

Type RM Length L Ch R = 1 ,8503.2,1322,1315.1,1308.1
XS GIS Cut Line= 2
     2126412.357      297115.382     2131163.811      295946.681
#Sta/Elev= 30
     9.9  902.11   198.9  873.11   328.2  858.92   745.9  787.28   865.2  776.55
   934.9  778.32  1014.4  767.06  1352.6  767.45  1432.1  761.57  1999.0  757.26
  2128.3  751.09  2367.0  756.27  2391.7  753.16  2406.7  750.10  2436.6  749.70
  2575.8  753.89  2625.6  750.46  2735.0  756.97  2784.7  779.04  2804.6  781.48
  3361.5  778.49  3689.7  781.28  3968.2  788.99  4097.5  798.05  4187.0  819.53
  4266.5  845.20  4465.4  886.70  4584.8  891.02  4743.9  880.60  4893.1  877.11
#Mann= 3 , 0 , 0
       0     0.1       0  2391.7   0.045       0  2406.7     0.1       0
Bank Sta=  2391.7,  2406.7
Exp/Cntr=0.3,0.1

Type RM Length L Ch R = 1 ,7188.1,1214.3,1212.2,1210.3
XS GIS Cut Line= 2
     2127152.248      299036.750     2131093.018      296154.947
#Sta/Elev= 30
     9.9  904.44   129.3  874.81   169.0  872.03   298.3  902.63   437.5  913.65
   586.6  893.02   765.6  859.41  1133.5  807.86  1153.4  801.09  1193.2  770.14
  1352.3  760.77  1700.3  753.91  2863.6  755.28  3122.1  752.05  3185.3  741.99
  3200.3  739.38  3211.6  739.08  3251.4  739.48  3291.2  749.74  3420.4  747.34
  3430.4  751.74  3460.2  781.63  3649.1  775.59  3937.5  781.69  4007.1  777.50
  4295.4  790.76  4434.6  820.12  4563.9  864.89  4812.5  889.66  4882.1  908.89
#Mann= 3 , 0 , 0
       0     0.1       0  3185.3   0.045       0  3200.3     0.1       0
Bank Sta=  3185.3,  3200.3
Exp/Cntr=0.3,0.1