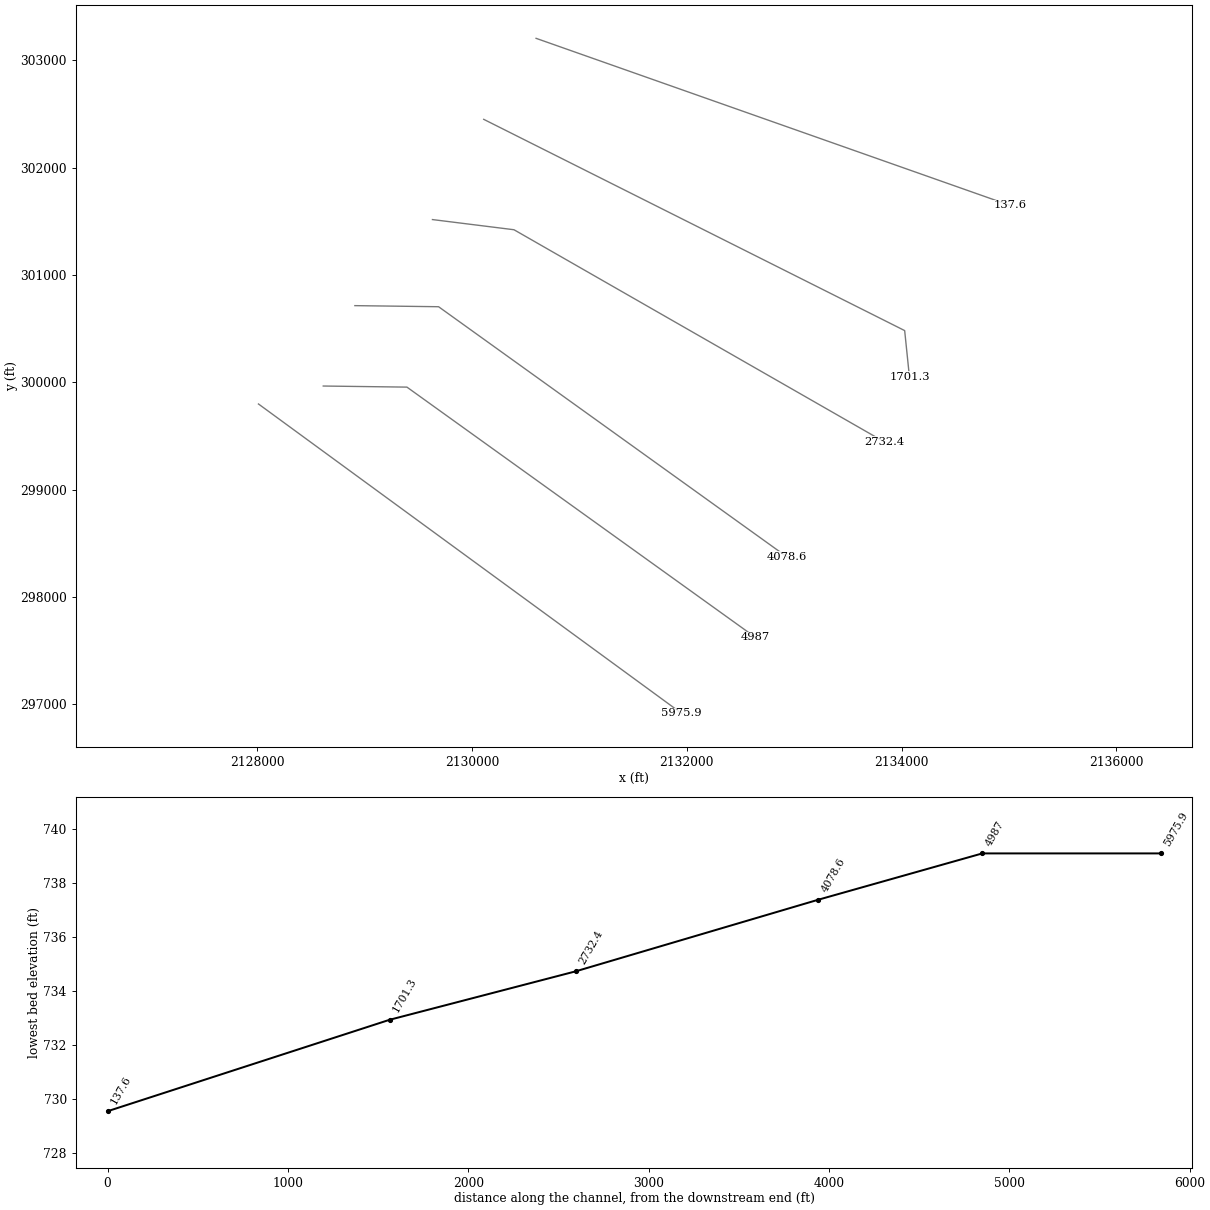
HEC-RAS study PTTRSNCR1.prj: PTTRSNCR1

--- PTTRSNCR1.g01 (geometry) --- (continued)

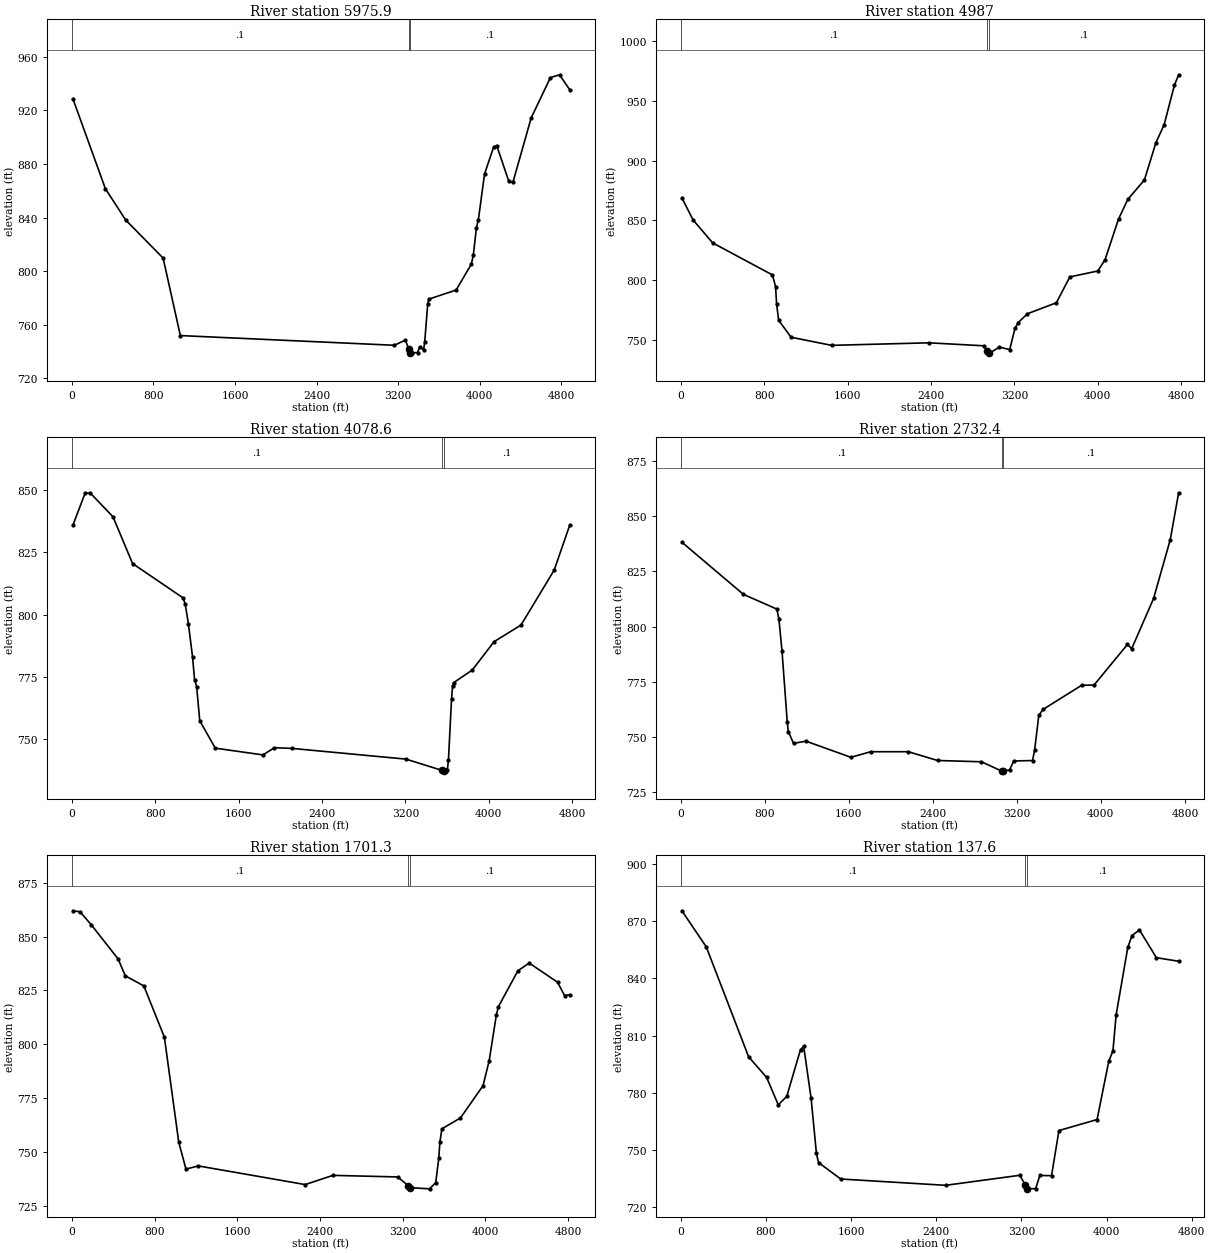
Type RM Length L Ch R = 1 ,5975.9,988.6,988.8,989.2
XS GIS Cut Line= 2
     2128010.881      299797.696     2131951.651      296915.894
#Sta/Elev= 30
     9.9  928.73   328.1  861.68   527.0  838.27   894.9  809.79  1063.9  751.97
  3161.9  744.73  3271.3  748.61  3303.1  741.97  3318.1  739.14  3330.9  739.09
  3390.6  739.32  3410.5  743.59  3450.2  741.52  3460.2  747.06  3490.0  775.70
  3500.0  779.15  3768.4  785.95  3917.6  805.27  3937.5  812.22  3967.3  832.22
  3987.2  838.58  4046.8  872.49  4136.3  892.64  4166.2  893.80  4285.5  867.04
  4325.2  866.27  4504.2  914.32  4693.1  944.48  4782.6  946.58  4882.1  935.44
#Mann= 3 , 0 , 0
       0     0.1       0  3303.1   0.045       0  3318.1     0.1       0
Bank Sta=  3303.1,  3318.1
Exp/Cntr=0.3,0.1

Type RM Length L Ch R = 1 ,4987,906.3,908.4,910.2
XS GIS Cut Line= 3
     2128614.076      299964.979     2129393.627      299954.809
     2132639.050      297623.835
#Sta/Elev= 30
     9.9  868.82   118.4  850.24   305.9  831.11   879.0  804.30   908.8  794.49
   918.8  779.89   938.7  766.32  1057.9  752.15  1445.6  745.36  2379.9  747.48
  2906.7  744.99  2939.6  740.62  2954.6  739.18  2966.4  739.09  3055.8  743.87
  3155.2  741.83  3204.9  759.47  3234.7  764.25  3324.2  771.78  3602.5  781.02
  3731.7  802.66  4000.1  807.60  4069.7  817.09  4198.9  851.10  4288.3  867.59
  4447.4  883.85  4556.7  914.86  4636.2  930.01  4735.6  963.36  4775.4  971.87
#Mann= 3 , 0 , 0
       0     0.1       0  2939.6   0.045       0  2954.6     0.1       0
Bank Sta=  2939.6,  2954.6
Exp/Cntr=0.3,0.1

Type RM Length L Ch R = 1 ,4078.6,1345.1,1346.3,1347.5
XS GIS Cut Line= 3
     2128908.701      300713.821     2129688.251      300703.651
     2132933.674      298372.677
#Sta/Elev= 30
     9.9  835.89   128.3  848.90   177.6  848.76   394.7  839.26   582.2  820.52
  1067.9  806.71  1087.7  804.14  1117.6  796.46  1157.3  783.15  1177.2  773.96
  1197.1  771.06  1226.9  757.45  1376.0  746.47  1833.2  743.77  1942.6  746.66
  2111.5  746.38  3204.9  742.08  3553.8  737.52  3568.8  737.40  3592.6  737.38
  3602.5  737.90  3612.4  741.63  3642.3  766.35  3652.2  771.32  3662.1  772.75
  3841.1  777.80  4049.8  789.18  4308.2  795.83  4626.3  817.84  4775.4  835.84
#Mann= 3 , 0 , 0
       0     0.1       0  3553.8   0.045       0  3568.8     0.1       0
Bank Sta=  3553.8,  3568.8
Exp/Cntr=0.3,0.1

Type RM Length L Ch R = 1 ,2732.4,1018.5,1031.1,1043.7
XS GIS Cut Line= 3
     2129631.190      301515.456     2130390.428      301420.772
     2133839.766      299444.483
#Sta/Elev= 30
     9.9  838.15   596.2  814.55   914.2  807.90   934.1  803.36   963.9  788.77
  1013.6  756.69  1023.5  752.48  1073.2  747.18  1192.5  748.14  1619.8  740.85
  1808.7  743.38  2166.4  743.38  2444.7  739.41  2862.1  738.83  3051.0  734.73
  3056.8  734.73  3071.8  734.74  3130.5  735.13  3170.2  739.20  3349.1  739.38
  3369.0  744.00  3408.7  759.78  3448.5  762.49  3816.2  773.41  3935.5  773.57
  4253.5  791.93  4293.3  789.96  4502.0  812.69  4661.0  839.34  4740.5  860.51
#Mann= 3 , 0 , 0
       0     0.1       0  3056.8   0.045       0  3071.8     0.1       0
Bank Sta=  3056.8,  3071.8
Exp/Cntr=0.3,0.1

Type RM Length L Ch R = 1 ,1701.3,1575.5,1563.7,1552.7
XS GIS Cut Line= 3
     2130108.620      302449.153     2134028.907      300481.322
     2134073.042      300052.821
#Sta/Elev= 30
     9.9  861.96    79.6  861.46   189.0  855.39   447.6  839.60   517.2  831.76
   696.3  827.11   895.2  803.32  1034.4  754.54  1104.1  742.10  1223.4  743.58
  2257.9  734.92  2526.4  739.19  3153.1  738.46  3256.7  734.35  3271.7  733.50
  3461.4  732.94  3521.1  735.83  3550.9  747.34  3560.9  754.46  3580.8  760.80
  3759.8  765.80  3978.6  780.80  4038.3  792.39  4108.0  813.73  4127.8  817.50
  4316.8  834.16  4425.6  837.70  4699.7  828.82  4768.3  822.59  4817.2  823.07
#Mann= 3 , 0 , 0
       0     0.1       0  3256.7   0.045       0  3271.7     0.1       0
Bank Sta=  3256.7,  3271.7
Exp/Cntr=0.3,0.1

Type RM Length L Ch R = 1 ,137.6,122.8,137.6,151.5
XS GIS Cut Line= 2
     2130596.183      303203.593     2135007.264      301648.500
#Sta/Elev= 30
    10.0  875.49   238.8  856.57   636.9  798.86   806.1  788.04   915.5  773.64
   995.1  778.05  1124.5  802.64  1154.4  804.31  1224.0  777.13  1273.8  748.25
  1293.7  743.36  1502.7  734.71  2487.9  731.41  3184.5  736.67  3235.6  731.66
  3244.2  729.56  3250.6  729.65  3333.7  729.64  3373.5  736.59  3483.0  736.46
  3552.7  760.15  3910.9  765.92  4020.4  796.40  4060.2  802.03  4090.0  820.83
  4199.5  856.25  4239.3  862.51  4309.0  865.43  4468.2  850.88  4677.2  848.99
#Mann= 3 , 0 , 0
       0     0.1       0  3235.6   0.045       0  3250.6     0.1       0
Bank Sta=  3235.6,  3250.6
Exp/Cntr=0.3,0.1